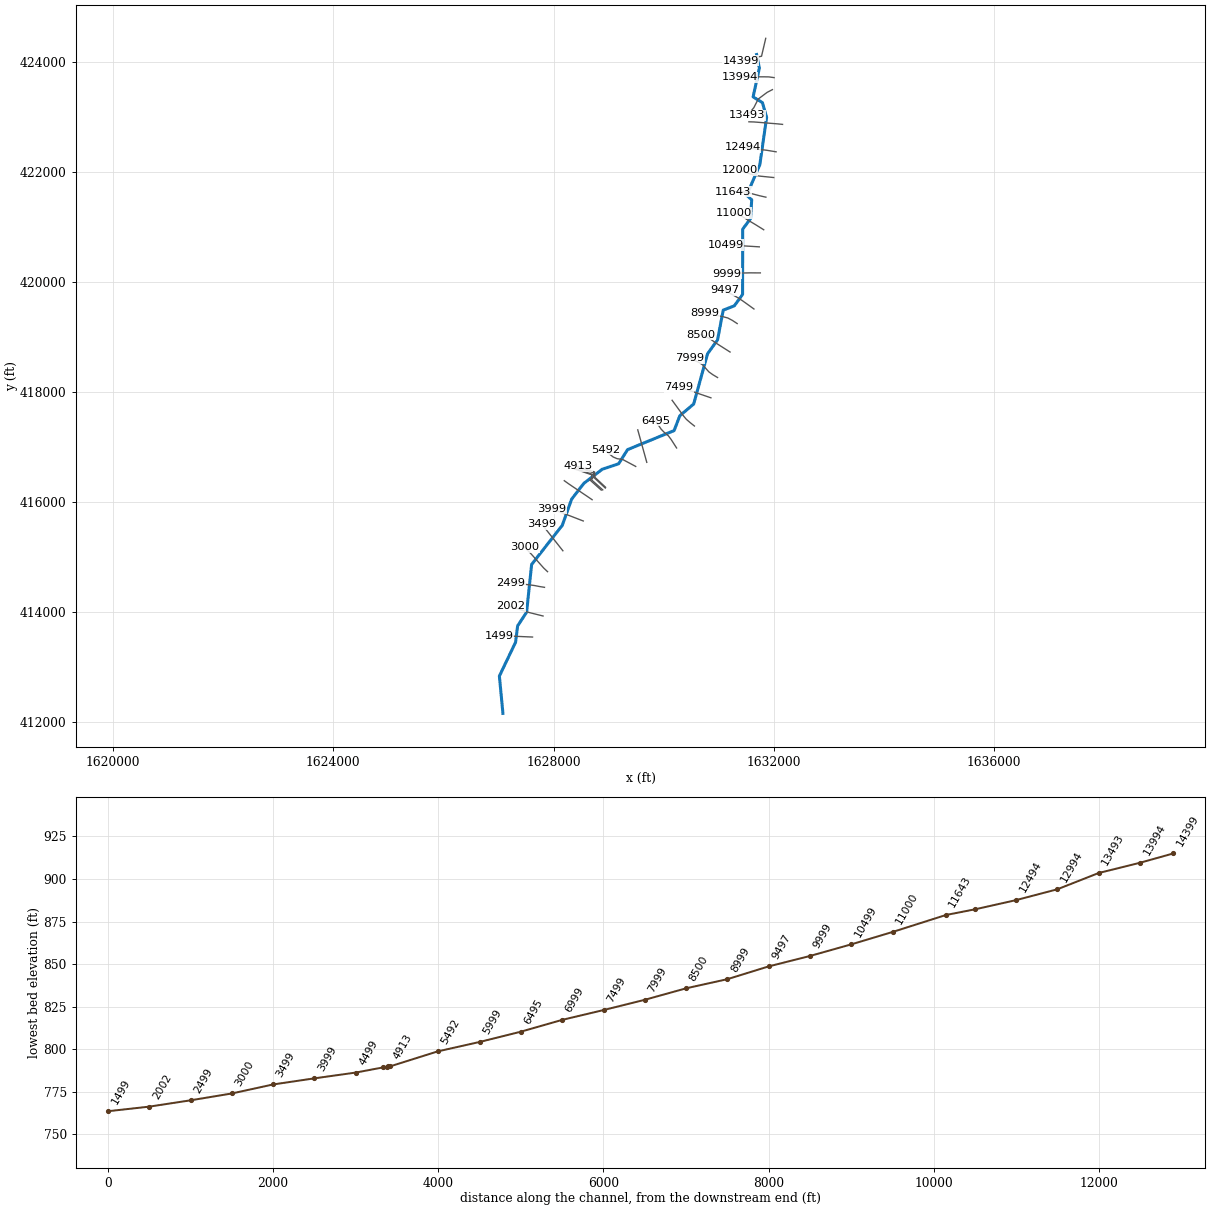
--- SCHDLRRN.prj (project) ---

Proj Title=SCHDLRRN
Current Plan=p01
Default Exp/Contr=0,0
English Units
Geom File=g01
Flow File=f01
Plan File=p01
BEGIN DESCRIPTION:
---------- MODELED AS PART OF WVEMD CTP PROGRAM, 2023----------
Stream Name: Scheidler Run
Flood Zone:  AFH
Wetzel County, WV
HEC-RAS Version: RAS 6.3
Vertical Datum: NAVD88
Projection: NAD 1983 StatePlane West Virginia S FIPS 4702 (US Feet)
Terrain: 1-meter West Virginia FEMA R3 South Central (collected 2018-2020)
Land Use: 2019 NLCD
Hydrologic Method:
WV SIR2010-5033 regression equations
Additional Model Notes:
Leveraged XS
END DESCRIPTION:
DSS Export Rating Curves= 0
DSS Export Rating Curve Sorted= 0
DSS Export Volume Flow Curves= 0
DXF OffsetX= 0
DXF OffsetY= 0
DXF ScaleX= 0
DXF ScaleY= 0

--- SCHDLRRN.p01 (plan) ---

Plan Title=Floodplain
Program Version=6.30
Short Identifier=Floodplain
Geom File=g01
Flow File=f01
Subcritical Flow
K Sum by GR= 0
Std Step Tol= 0.01
Critical Tol= 0.01
Num of Std Step Trials= 20
Max Error Tol= 0.3
Flow Tol Ratio= 0.001
Split Flow NTrial= 30
Split Flow Tol= 0.02
Split Flow Ratio= 0.02
Log Output Level= 0
Friction Slope Method= 1
Unsteady Friction Slope Method= 2
Unsteady Bridges Friction Slope Method= 1
Parabolic Critical Depth
Global Vel Dist= 0 , 0 , 0
Global Log Level= 0
CheckData=True
Encroach Param=-1 ,0,0, 0
Mapping Interval=1HOUR
Computation Time Step Use Courant=        0
Computation Time Step Use Time Series=    0
Computation Time Step Count To Double=0
Computation Time Step Max Doubling=0
Computation Time Step Max Halving=0
Computation Time Step Residence Courant=0
Run HTab= 0
Run UNet= 0
Run Sediment= 0
Run PostProcess= 0
Run WQNet= 0
Run RASMapper= 0
UNET Theta= 0
UNET Theta Warmup= 0
UNET ZTol= 0
UNET ZSATol= 0
UNET MxIter= 0
UNET Max Iter WO Improvement= 0
UNET MaxInSteps= 0
UNET DtIC= 0
UNET DtMin= 0
UNET MaxCRTS= 0
UNET WFStab= 0
UNET SFStab= 0
UNET WFX= 1
UNET SFX= 1
UNET Gravity=32.17405
UNET 1D Methodology=Finite Difference
UNET DSS MLevel= 1
UNET Pardiso=0
UNET DZMax Abort= 0
UNET Use Existing IB Tables= 0
UNET Froude Reduction=False
UNET Froude Limit= 0
UNET Froude Power= 0
UNET D1 Cores= 0
UNET WindReference=Eulerian
UNET WindDragFormulation=Hsu (1988)
UNET D2 Coriolis=0
UNET D2 Cores= 0
UNET D2 Theta= 1
UNET D2 Theta Warmup= 1
UNET D2 Z Tol= 0.01
UNET D2 Volume Tol= 0.01
UNET D2 Max Iterations= 20
UNET D2 Equation= 0
UNET D2 RampUpFraction=0.1
UNET D2 TimeSlices= 1
UNET D2 Turbulence Formulation=Non-Conservative (original)
UNET D2 Eddy Viscosity=0.3
UNET D2 Transverse Eddy Viscosity=0.1
UNET D2 Smagorinsky Mixing=0
UNET D2 BCVolumeCheck=0
UNET D2 Cores=0
UNET D2 SolverType=PARDISO (Direct)
UNET D2 Minimum Iterations= 3
UNET D2 Maximum Iterations= 30
UNET D2 Restart Number= 10
UNET D2 Relaxation Coeff=1.3
UNET D2 SOR Precondition Iterations= 10
UNET D2 ILUT Maximum Fill= 8
UNET D2 ILUT Tolerance=1E-08
UNET D2 Convergence Tolerance=0.00001
UNET D1D2 MaxIter= 0
UNET D1D2 ZTol=0.01
UNET D1D2 QTol=0.1
UNET D1D2 MinQTol=1
Write IC File= 0
Write IC File at Fixed DateTime=0
Write IC File at Sim End=0
Echo Input=False
Echo Parameters=False
Echo Output=False
Write Detailed= 0
HDF Write Warmup=0
HDF Write Time Slices=0
HDF Flush=0
HDF Compression= 1
HDF Chunk Size= 1
HDF Spatial Parts= 1
HDF Use Max Rows=0
HDF Fixed Rows= 1
Calibration Method= 0
Calibration Iterations= 20
Calibration Max Change=0.05
Calibration Tolerance=0.2
Calibration Maximum=1.5
Calibration Minimum=0.5
Calibration Optimization Method= 1
WQ AD Non Conservative
WQ ULTIMATE=-1
WQ Max Comp Step=1HOUR
WQ Output Interval=15MIN
WQ Output Selected Increments= 0
WQ Output face flow=0
WQ Output face velocity=0
WQ Output face area=0
WQ Output face dispersion=0
WQ Output cell volume=0
WQ Output cell surface area=0
WQ Output cell continuity=0
WQ Output cumulative cell continuity=0
WQ Output face conc=0
WQ Output face dconc_dx=0
WQ Output face courant=0
WQ Output face peclet=0
WQ Output face adv mass=0
WQ Output face disp mass=0
WQ Output cell mass=0
WQ Output cell source sink temp=0
WQ Output nsm pathways=0
WQ Output nsm derived pathways=0
WQ Create Restart=0
WQ Fixed Restart=0
WQ System Summary=0
WQ Write To DSS=0
Sorting and Armoring Iterations= 10
XS Update Threshold= 0.02
Bed Roughness Predictor= 0
Hydraulics Update Threshold= 0.02
Energy Slope Method= 1
Volume Change Method= 1
Sediment Retention Method= 0
Sediment TS Multiplier= 1
Warm Up Method= 0
XS Weighting Method= 0
Number of US Weighted Cross Sections= 1
Number of DS Weighted Cross Sections= 1
Upstream XS Weight=0
Main XS Weight=1
Downstream XS Weight=0
Number of DS XS's Weighted with US Boundary= 1
Upstream Boundary Weight= 1
Weight of XSs Associated with US Boundary= 0
Number of US XS's Weighted with DS Boundary= 1
Downstream Boundary Weight= 0.5
Weight of XSs Associated with DS Boundary= 0.5
Percentile Method= 0
Sediment Output Level= 3
Mass or Volume Output= 0
Output Increment Type= 1
Profile and TS Output Increment= 1
Transport Output Increment 1
XS Output Flag= 0
XS Output Increment= 10
Read HDF5 Sediment Hotstart= 0
Sediment Hotstart Type= 0
Write Gradation File= 0
Read Gradation Hotstart= 0
Write HDF5 File= 1
Write Binary Output= 1
Write DSS Sediment File= 0
DSS Sediment Output Type= 1
SV Curve= 0
Specific Gage Flag= 0
Subcell Erosion Methods= 0
Subcell Deposition Methods= 0
Advection Scheme= 1
Matrix Solver= 0
Implicit Weighting Factor= 1
Maximum Outer Loop Convergence Iterations= 5
Convergence Maximum Absolute= 0.001
Convergence RMSE= 0.0001
Grain Fractions Max Abs Error= 0.001
Max Subgrid Regions= 1
Max Subgrid Length Scale= 3.402823E+38
Initial Layer Thickness= 3.402823E+38
Min Layer Thickness= 3.402823E+38
Max Layer Thickness= 3.402823E+38
Number of Layers= 5

--- SCHDLRRN.f01 (steady flow) ---

Flow Title=Flow
Program Version=6.31
Number of Profiles= 1
Profile Names=F01pct
River Rch & RM=SCHDLRRN,Main            ,14399
     722
River Rch & RM=SCHDLRRN,Main            ,11643
     809
River Rch & RM=SCHDLRRN,Main            ,8500
     902
River Rch & RM=SCHDLRRN,Main            ,4913
    1470
Boundary for River Rch & Prof#=SCHDLRRN,Main            , 1
Up Type= 0
Dn Type= 3
Dn Slope=0.00732
DSS Import GetInterval= 0
DSS Import GetPeak= 0
DSS Import FillOption= 0

--- SCHDLRRN.g01 (geometry) ---

Geom Title=Geometry
Program Version=6.31

River Reach=SCHDLRRN        ,Main
Reach XY= 30
1631687.88868313424127.923883549     1631738.303      423882.509
     1631624.569      423358.625     1631793.748      423253.421
     1631869.807      422986.147     1631746.833       422127.46
     1631507.992      421571.588     1631598.979      421487.709
     1631577.654      421145.798     1631434.777      420954.584
     1631433.355      419770.334     1631283.369      419562.059
     1631081.492      419483.157     1630978.421      418943.634
     1630796.855      418690.316     1630545.224      417777.879
     1630293.046      417563.993     1630189.658      417294.857
     1629343.958       416948.59     1629183.133      416692.583
     1628885.005      416592.477     1628550.773       416336.47
     1628328.681      416048.735     1628159.103      415573.371
     1627602.233      414862.239     1627511.427      413994.658
     1627348.413      413746.856     1627311.216      413449.822
     1627016.916      412834.419     1627081.354      412156.699

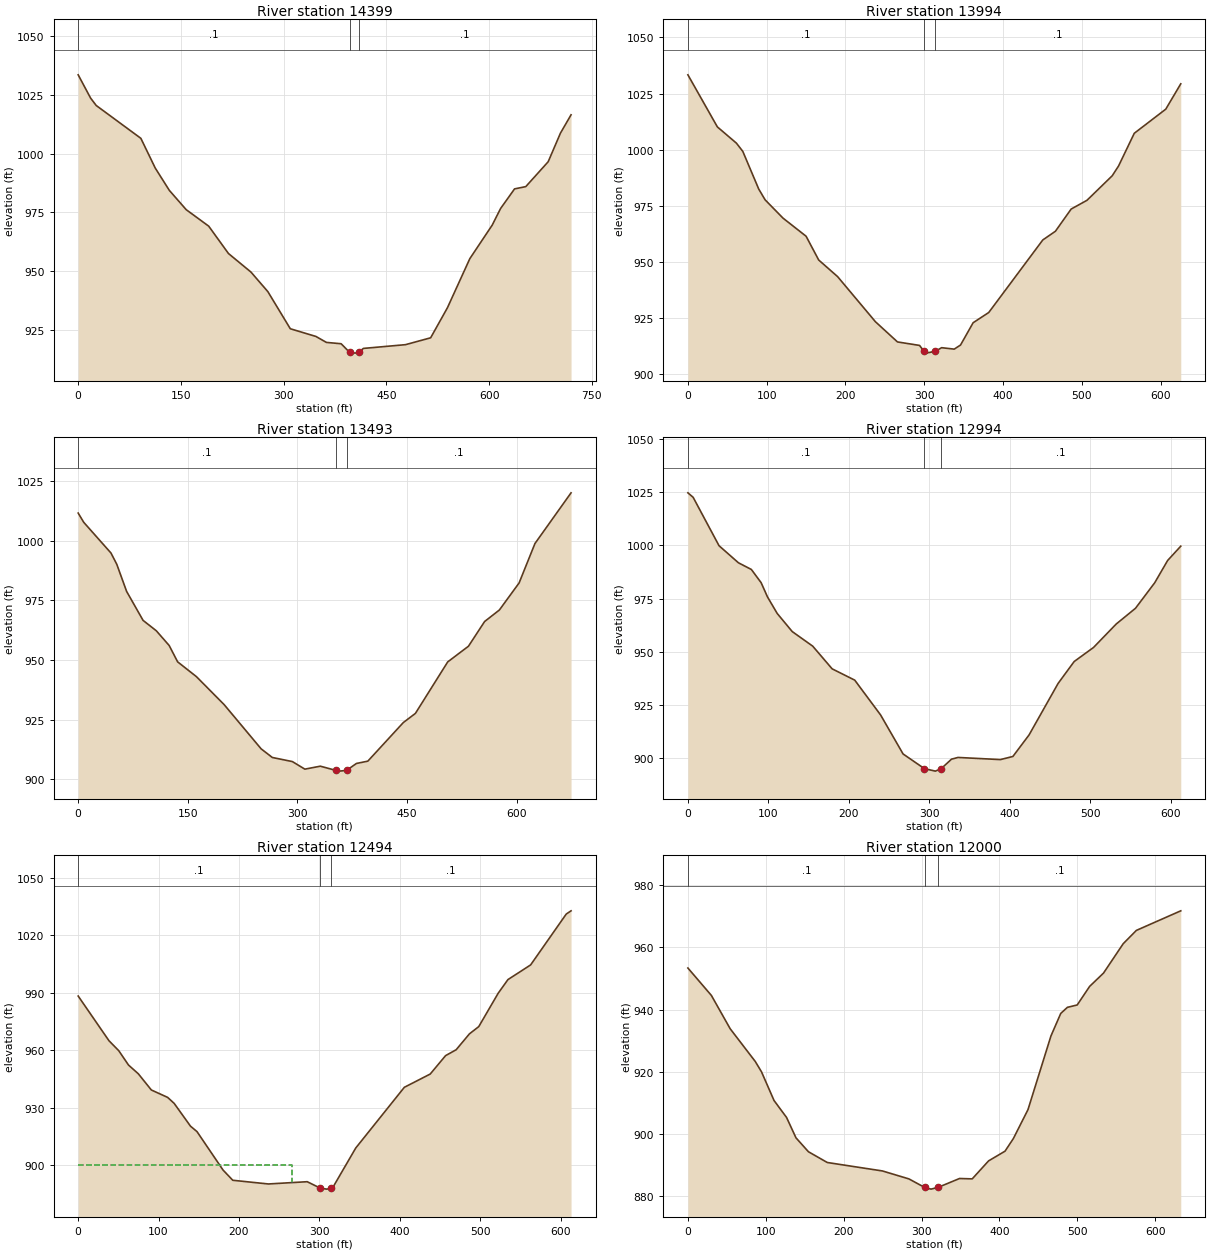
Type RM Length L Ch R = 1 ,14399   ,404.5,405.3,402
XS GIS Cut Line= 3
1631853.47904432 424422.118861421631777.39297402424097.372063266
1631399.37738279 424018.96016044
#Sta/Elev= 30
       0 1033.59    18.1 1023.69    26.3 1020.53    91.5 1006.53   112.5  993.87
   133.1  984.34   157.7  976.13   190.6  969.09   219.4  957.44   252.2  949.55
   276.9  941.21   309.7  925.38   347.1   922.1   362.4  919.56   383.9  918.99
   396.2  915.37   404.3  914.99  409.38   915.4   416.5     917   477.8  918.59
   514.6  921.52   539.1  934.32   571.8  955.24   604.5  969.55   616.7  976.61
   637.1  984.98   653.5  985.95   686.2  996.55   704.1 1008.73   719.6 1016.55
#Mann= 3 ,-1,0
       0      .1       0   396.2    .045       0  409.38      .1       0
Bank Sta=396.2,409.38
XS Rating Curve= 0 ,0
Exp/Cntr(USF)=0,0
Exp/Cntr=0.3,0.1

Type RM Length L Ch R = 1 ,13994   ,488.9,500.5,505.5
XS GIS Cut Line= 6
1632005.17384976423708.3402172631631911.70684509423721.354298845
1631824.20702009423722.8113169221631649.20704201423722.811316922
1631571.93324642423714.6833804251631381.09996668423710.868099332
#Sta/Elev= 30
       0 1033.36    37.4 1010.18    61.6 1002.94    69.7  999.27    89.9  982.52
      98  977.72   120.7  969.58     150  961.52     166  950.94     190  943.54
     238  923.46     266  914.47     294  912.92   299.7  910.26     302  909.49
     314  910.29     322  911.91     338  911.27     346  913.09     362  923.02
   381.8  927.57   450.4  959.86   466.4  963.73   486.4  973.62   506.5  977.52
   538.5  988.43   546.5  992.75   566.5 1007.34   606.5 1018.09   625.5 1029.36
#Mann= 3 ,-1,0
       0      .1       0   299.7    .045       0     314      .1       0
Bank Sta=299.7,314
XS Rating Curve= 0 ,0
Exp/Cntr(USF)=0,0
Exp/Cntr=0.3,0.1

Type RM Length L Ch R = 1 ,13493   ,509.2,499.5,490
XS GIS Cut Line= 6
1631974.89569509423490.3616505861631878.08552125423439.884061262
1631717.02252318423318.9725576791631637.40719683423161.982058004
1631580.01886018423092.992694676 1631507.7312751423026.730688095
#Sta/Elev= 30
       0 1011.51     7.6 1007.64    44.9  994.77    52.8  990.08    66.3   978.7
    88.8  966.58   106.9  962.23   124.5  956.07   136.1  949.22   161.8  943.03
   199.7  931.33   250.4  912.79   265.7  909.18   293.1  907.47   310.2   904.3
   331.4  905.54  352.51903.7855   357.7  903.47   367.3  903.79   380.8  906.68
   396.4  907.65   444.9  923.79   461.5  927.64   505.7  949.19   534.1  955.76
   556.2   966.1   576.4  970.92   603.4  982.25   625.1  998.76   674.5 1019.98
#Mann= 3 ,-1,0
       0      .1       0  352.51    .045       0   367.3      .1       0
Bank Sta=352.51,367.3
XS Rating Curve= 0 ,0
Exp/Cntr(USF)=0,0
Exp/Cntr=0.3,0.1

Type RM Length L Ch R = 1 ,12994   ,501.1,500,499.3
XS GIS Cut Line= 6
1632158.59020959422858.5568118391632065.32071109422868.278577179
1631903.35253109 422881.411424921631728.92473035422895.554441258
1631641.71099401422902.6262775061631547.87489559422905.358555511
#Sta/Elev= 30
       0 1024.71     6.5 1022.62    38.7  999.86    62.8  991.84    78.9  988.69
      91  982.51      99  975.75     111  968.03   129.7  959.51   155.2  952.65
   179.3     942   207.4  936.69   239.5  920.36   267.5     902  294.09895.0782
   307.7  893.93  314.86895.0821   327.7  899.55   335.8  900.36   388.4  899.35
     404  900.82   424.1  910.93   460.2  935.13   480.2  945.44   504.3  952.06
   532.4  963.04   556.4  970.45   580.3  982.44   596.4  992.93   612.7  999.64
#Mann= 3 ,-1,0
       0      .1       0  294.09    .045       0  314.86      .1       0
Bank Sta=294.09,314.86
XS Rating Curve= 0 ,0
Exp/Cntr(USF)=0,0
Exp/Cntr=0.3,0.1

Type RM Length L Ch R = 1 ,12494   ,494.1,494.1,493
XS GIS Cut Line= 6
1632041.92902559422360.2658136791631948.94135067422375.564995676
 1631862.4234791422389.6801249241631787.92854933422398.370068178
 1631527.1974435422428.7899548411631434.07886334422439.654106334
#Sta/Elev= 30
       0  988.31    38.3     965    50.5  959.78    62.6  952.31    74.8  947.75
      91   939.3   111.3  935.42   119.4   932.3   139.7  920.42   147.8  917.57
   180.2  897.52   192.3  892.18   236.6  890.25   284.9  891.43     301  888.11
   309.1  887.56   314.8888.1083   317.1  888.68   345.3  909.03   405.7  940.69
   437.9  947.61     457  957.21   470.2   960.3   486.7  968.58   498.3  972.37
   522.5  989.81   534.6   996.9   562.8 1004.55   607.1 1031.09   613.1 1032.78
#Mann= 3 ,-1,0
       0      .1       0     301    .045       0   314.8      .1       0
#XS Ineff= 2 , 0
          265.71  900.36
Permanent Ineff=
       F       F
Bank Sta=301,314.8
XS Rating Curve= 0 ,0
Exp/Cntr(USF)=0,0
Exp/Cntr=0.3,0.1

Type RM Length L Ch R = 1 ,12000   ,356.9,356.7,354.9
XS GIS Cut Line= 6
1631998.17812884421892.9176670011631743.33579075421918.768993258
1631639.66080126421936.8906761711631561.99560225421962.222974584
1631474.21625026 421991.615632341631382.19740543422023.143784508
#Sta/Elev= 30
       0  953.36    30.2  944.52    54.3  933.81    86.5  923.28    94.5  919.96
   110.6  910.72   126.7  905.26   138.8   898.7   154.8  894.22     179  890.76
   249.8  888.04   283.8  885.48   304.1  882.73   312.2  882.19  321.22882.7437
   348.8  885.61   365.1  885.49   386.1  891.28   407.2   894.4   417.9  898.45
   436.7  907.77   466.2  931.49   478.8  938.75   487.3   940.7   499.9  941.47
   515.9  947.45   533.7  951.73     559  961.19   575.9  965.47   632.9  971.77
#Mann= 3 ,-1,0
       0      .1       0   304.1    .045       0  321.22      .1       0
Bank Sta=304.1,321.22
XS Rating Curve= 0 ,0
Exp/Cntr(USF)=0,0
Exp/Cntr=0.3,0.1

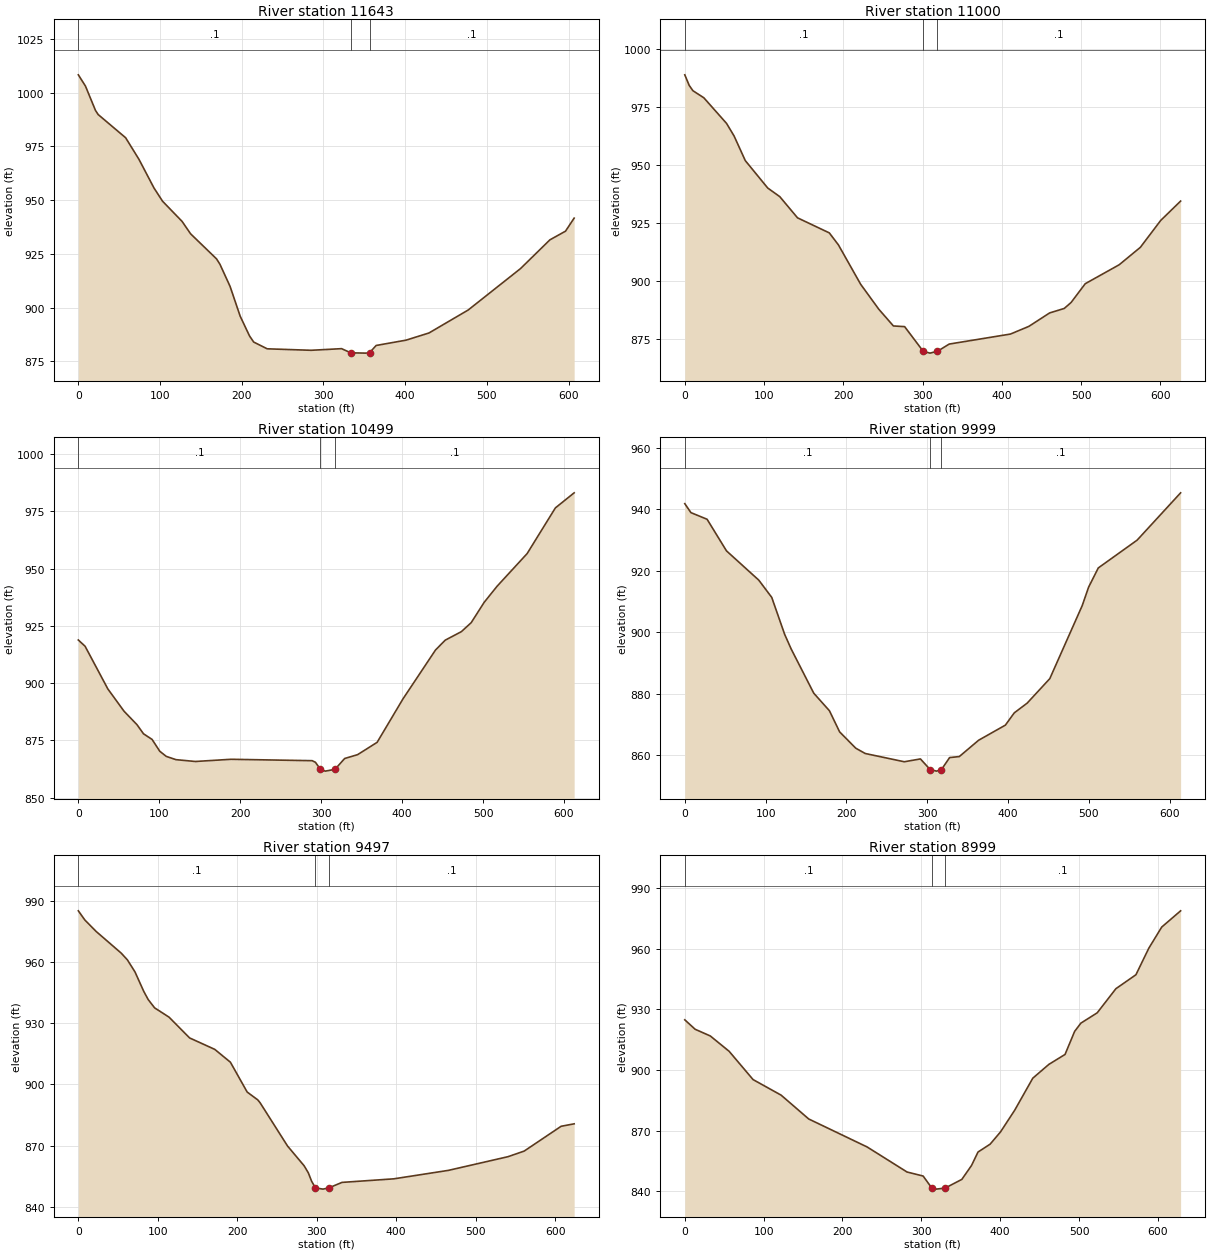
Type RM Length L Ch R = 1 ,11643   ,636.6,642.9,631.1
XS GIS Cut Line= 5
1631856.58418463  421535.91107651631744.22200693421561.573337584
1631549.58697484421612.4979158781631495.18220318421631.227427435
1631262.41553945421637.761732649
#Sta/Elev= 30
       0 1008.31     8.7 1003.09      21  991.74    24.3  989.82    57.9  979.03
    74.3  968.92    92.6  955.65   103.1  949.48     127  940.09   137.4  934.32
   169.1  922.68   173.3  920.16   185.7  909.86   198.1  895.97   209.5  886.81
   214.6  883.96   231.1  880.81   284.9  880.12   322.2  880.88   333.4  878.94
   352.2   878.8  356.34 878.974   364.5  882.36   401.1  884.84   429.1  888.17
   477.1  898.86   541.1  918.12   577.1  931.51   596.2  935.55   606.8  941.63
#Mann= 3 ,-1,0
       0      .1       0   333.4    .045       0  356.34      .1       0
Bank Sta=333.4,356.34
XS Rating Curve= 0 ,0
Exp/Cntr(USF)=0,0
Exp/Cntr=0.3,0.1

Type RM Length L Ch R = 1 ,11000   ,496.5,500.8,504.9
XS GIS Cut Line= 6
1631816.89994809 420944.316217751631663.00950783 421040.01123634
1631512.76276109 421129.782382251631449.61360918421170.855134755
 1631368.1173811421212.4613507541631272.66776884 421249.40615876
#Sta/Elev= 30
       0  988.79     5.6  984.21    10.3  981.93      24   978.9    52.7  967.85
    62.2  962.42    76.3  951.83   104.6  940.02   119.8   936.3   142.2  927.17
   182.3  920.68   193.8   915.5   221.8  898.56   244.6  887.84   263.1  880.59
   277.3  880.29   300.7  869.68   309.3  868.88  318.69869.6764   333.5  872.78
   410.8   877.1     434  880.41   460.2   886.2   478.6  888.13   487.2  890.68
   505.1  898.79   547.9  906.95   574.6  914.46   600.3  926.06   625.4  934.39
#Mann= 3 ,-1,0
       0      .1       0   300.7    .045       0  318.69      .1       0
Bank Sta=300.7,318.69
XS Rating Curve= 0 ,0
Exp/Cntr(USF)=0,0
Exp/Cntr=0.3,0.1

Type RM Length L Ch R = 1 ,10499   ,499.6,500.6,501.2
XS GIS Cut Line= 6
1631736.47983333420633.4392148411631642.91243517420639.285987929
 1631480.7290325420649.4221225081631306.06960492420660.337126926
1631218.64589526420664.2895468321631124.93414043420667.826613262
#Sta/Elev= 30
       0  918.86     8.4   916.1    36.4  897.52    56.5  887.74    72.5  881.86
    80.5   877.9    91.1  875.43   100.6  870.28   108.6  868.03   120.6   866.6
   144.6   865.8   188.7  866.76   288.9  866.15   292.9  865.45  299.04862.3945
     305  861.59     317  862.36     329   867.1     345  868.79   369.1  874.16
   401.1  893.17   441.2  914.47   453.2  918.78   473.2  922.51   485.3  926.42
   501.3  935.28   517.3  942.34   554.4  956.59   589.3  976.54   612.5  983.13
#Mann= 3 ,-1,0
       0      .1       0  299.04    .045       0     317      .1       0
Bank Sta=299.04,317
XS Rating Curve= 0 ,0
Exp/Cntr(USF)=0,0
Exp/Cntr=0.3,0.1

Type RM Length L Ch R = 1 ,9999    ,505.4,502,495
XS GIS Cut Line= 6
1631755.71667151420160.304006249 1631661.3923851420160.291539088
1631573.48573676420161.161944166 1631498.3592466420159.516934335
1631398.33516842420156.7682521791631142.34092976420148.388675749
#Sta/Elev= 30
       0  941.84     7.6  938.92    27.6  936.76    51.6  926.47    91.6  916.93
   107.6  911.32   123.6  899.28   131.6  894.55   159.6  880.13     179  874.42
   191.6  867.54   211.6  862.22   223.3   860.5   271.6  857.81   291.6  858.73
   303.6  855.28   311.6  854.76  317.62855.2646   327.7  859.17   339.7   859.5
   363.6  864.81   396.7  869.73   407.7  873.72   423.7   876.9   451.7  884.87
   491.9   908.7   499.7  914.64   511.7  920.91   559.8  929.97   613.6  945.37
#Mann= 3 ,-1,0
       0      .1       0   303.6    .045       0  317.62      .1       0
Bank Sta=303.6,317.62
XS Rating Curve= 0 ,0
Exp/Cntr(USF)=0,0
Exp/Cntr=0.3,0.1

Type RM Length L Ch R = 1 ,9497    ,492.9,497.9,499.1
XS GIS Cut Line= 6
1631639.48166776419504.4536119251631431.45682134419654.085530505
1631347.47700243419708.5864057541631281.76223885419745.667368338
1631204.96908534419788.8411665111631116.06571984419842.936530754
#Sta/Elev= 30
       0  985.23     8.2  980.73    22.5  975.08    54.1  964.42    61.8  961.12
    71.3  955.25    82.3  945.72    87.9  941.69      96   937.6   114.2  933.02
     140  922.84   171.7  917.22   191.4  910.91   212.5  896.26   225.9   892.4
   228.9  890.92   263.3  869.77   284.1  860.11   289.4  856.65   293.6  852.48
   298.4  849.22   307.9  848.61   315.4  849.23   331.8  851.91     397  853.66
   465.8  857.82   540.7  864.53   561.1  867.28   607.6  879.46     624  880.67
#Mann= 3 ,-1,0
       0      .1       0   298.4    .045       0   315.4      .1       0
Bank Sta=298.4,315.4
XS Rating Curve= 0 ,0
Exp/Cntr(USF)=0,0
Exp/Cntr=0.3,0.1

Type RM Length L Ch R = 1 ,8999    ,500.7,498.3,491.9
XS GIS Cut Line= 6
1631335.05248658419239.5053229181631248.32726634419296.655143008
1631165.53642142419340.4657509181631093.09496526419360.427653253
1630995.34548885419381.5319417571630744.59238142419434.321862429
#Sta/Elev= 30
       0  924.85    13.1  920.18    32.3  916.88    56.2   909.3    86.6   895.3
   122.2   887.6   157.2  875.82   231.3  861.98   281.9   849.6   302.3  847.61
   313.3841.6866   318.7  841.14   330.1  841.64   351.4  845.95   363.7  852.84
   371.9  859.47   387.3  863.38   400.5  869.45   418.5  880.19   441.4  895.99
   461.8  902.82   482.3  907.73   494.5  919.15   502.4  923.21   523.1  928.31
   546.8  940.24   572.2  947.13   588.5  960.22   604.9   970.7   628.9  978.74
#Mann= 3 ,-1,0
       0      .1       0   313.3    .045       0   330.1      .1       0
Bank Sta=313.3,330.1
XS Rating Curve= 0 ,0
Exp/Cntr(USF)=0,0
Exp/Cntr=0.3,0.1

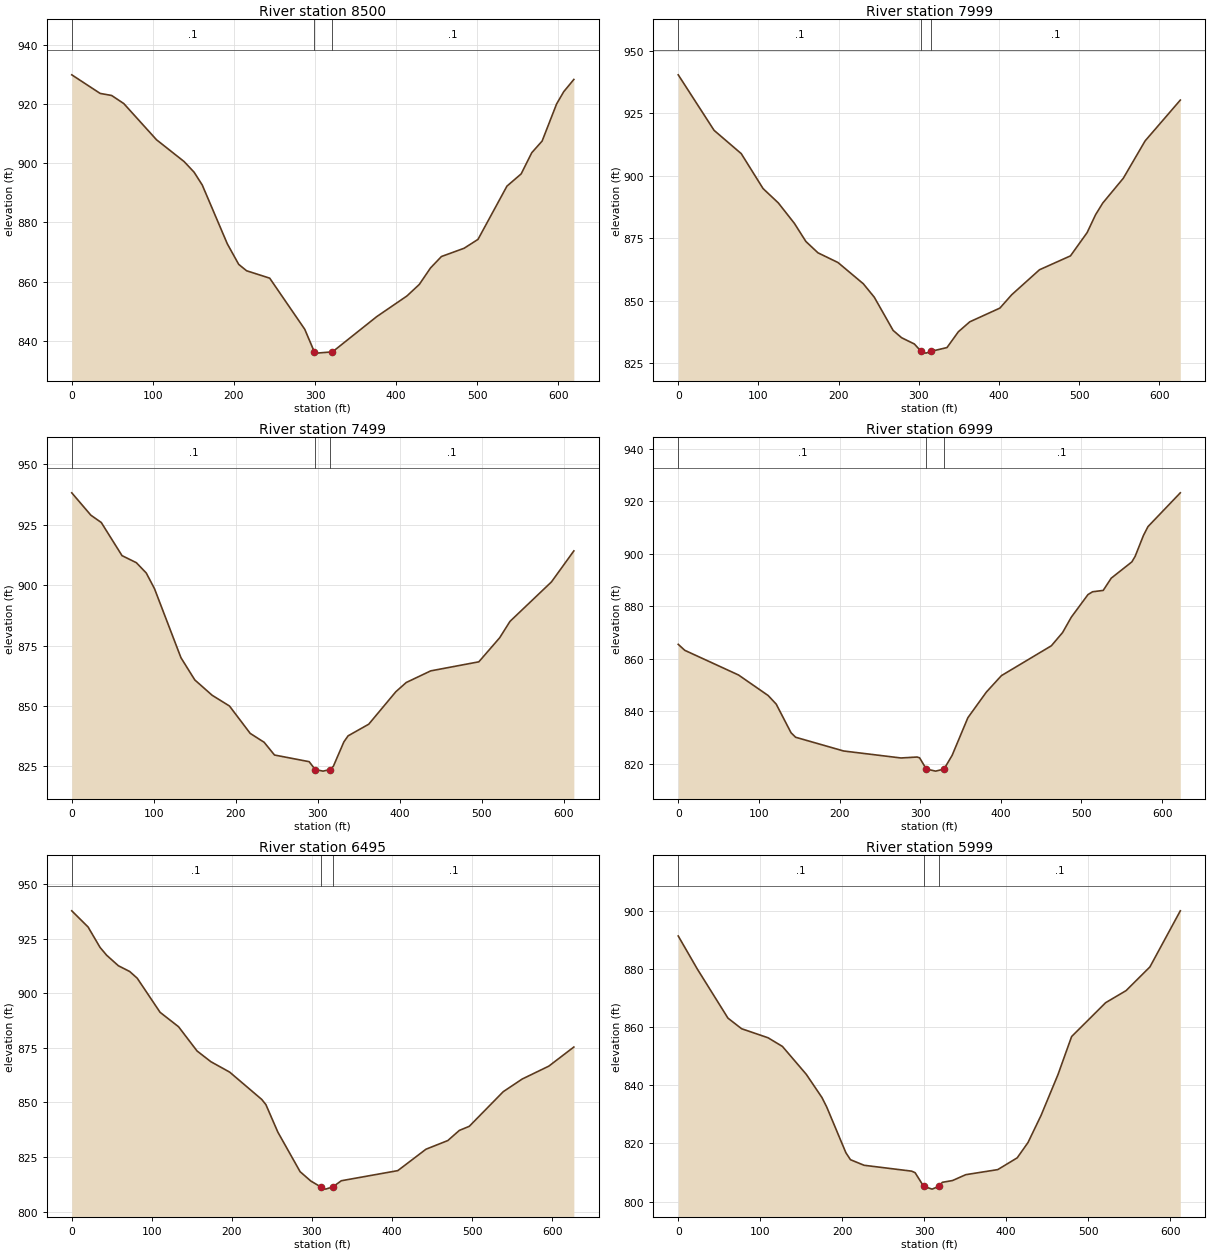
Type RM Length L Ch R = 1 ,8500    ,503.3,501.4,501.8
XS GIS Cut Line= 6
1631206.02059242418722.1270925851630989.83270459418859.701620594
1630907.00970751418915.8137130891630845.67780918418959.569859177
1630765.95913659419001.0933981691630676.64796351419040.693056509
#Sta/Elev= 30
       0  929.96      35  923.67    49.2  922.97    64.1  920.25   104.5  907.99
   138.6   900.6   150.9     897   160.9  892.69   191.9  872.74   205.9  865.82
   215.6  863.66   244.1  861.16   287.3  843.88  299.15 836.235   301.8  835.79
   321.5  836.21   376.1  848.14   413.4  855.14   428.6  859.03   442.4   864.6
   455.9  868.48   483.9  871.28     501  874.28   536.7   892.3   554.2  896.43
   567.3   903.6   580.1  907.56   597.9  920.09   606.7  924.24   619.2   928.4
#Mann= 3 ,-1,0
       0      .1       0  299.15    .045       0   321.5      .1       0
Bank Sta=299.15,321.5
XS Rating Curve= 0 ,0
Exp/Cntr(USF)=0,0
Exp/Cntr=0.3,0.1

Type RM Length L Ch R = 1 ,7999    ,495.6,500,502.4
XS GIS Cut Line= 6
1630978.49873775418259.1673885881630895.89522843418308.558365926
1630822.88290726418360.0743390021630706.12953185418490.458920762
 1630641.7661435418532.6442038421630471.74778275418614.065300837
#Sta/Elev= 30
       0  940.45    44.7  918.23    78.6   908.9   105.8  894.92   124.8  889.18
   144.9  880.98   159.2  873.74   174.3  869.19   199.2  865.32   230.8  856.82
   244.5  851.44     268  838.14   278.6   835.2   294.5   832.7   302.8  829.79
   308.9  829.04  315.74829.7823   335.2  831.27   349.4   837.6   363.6  841.57
   401.2  847.07   415.9  852.41   450.6  862.42   489.2  867.97     510   877.3
   520.5  884.44   529.5  889.13   555.1  899.05   582.3     914   626.2  930.34
#Mann= 3 ,-1,0
       0      .1       0   302.8    .045       0  315.74      .1       0
Bank Sta=302.8,315.74
XS Rating Curve= 0 ,0
Exp/Cntr(USF)=0,0
Exp/Cntr=0.3,0.1

Type RM Length L Ch R = 1 ,7499    ,504.8,500,491.9
XS GIS Cut Line= 6
1630858.13546142417890.4932571651630686.64269418417949.160134584
  1630521.063629418005.8047063351630450.10117251 418030.08057642
1630367.16269009418057.9673316781630278.18189692418087.501393333
#Sta/Elev= 30
       0  938.23    23.3  928.97      36  925.94    61.3  912.23    78.8   909.3
    90.9  905.02   100.9  898.56   133.2  869.96   150.1  860.76   171.2  854.42
   192.4  849.96   217.7  838.62   234.7  834.94   247.3  829.67   289.6  826.91
  297.01823.6616   306.5     823   315.3  823.66   319.2  825.06   331.9  835.07
   337.1  837.61   362.3  842.43   395.3  855.86     408  859.69   437.9  864.51
   496.6  868.26     522  878.21   534.6     885   585.2  901.35   612.5  914.18
#Mann= 3 ,-1,0
       0      .1       0  297.01    .045       0   315.3      .1       0
Bank Sta=297.01,315.3
XS Rating Curve= 0 ,0
Exp/Cntr(USF)=0,0
Exp/Cntr=0.3,0.1

Type RM Length L Ch R = 1 ,6999    ,500.8,503.9,506.6
XS GIS Cut Line= 6
1630558.47890851417378.0772872571630479.67263567417440.998093173
1630411.45787708417500.2827515011630363.22864284417557.936835676
1630304.31143785417638.7375270871630153.33536184417845.788622171
#Sta/Elev= 30
       0  865.55     8.1  863.27    74.7  853.88   111.5  846.05   121.5  842.78
   139.9  831.86   145.6  830.15   205.1  824.92   276.2  822.26   296.2  822.62
   299.3  822.32   307.7  818.02   319.2  817.25  329.59818.0359   339.6  823.23
   359.2  837.61   382.1  847.36   400.7  853.61   462.7     865   476.6  870.03
   487.4  875.88   508.1   884.5   513.8  885.57     527  886.09   536.9  890.74
   562.5  896.95   566.6  899.07   576.8  906.96   582.5  910.39   622.6  923.26
#Mann= 3 ,-1,0
       0      .1       0   307.7    .045       0  329.59      .1       0
Bank Sta=307.7,329.59
XS Rating Curve= 0 ,0
Exp/Cntr(USF)=0,0
Exp/Cntr=0.3,0.1

Type RM Length L Ch R = 1 ,6495    ,499.8,496.1,489.8
XS GIS Cut Line= 6
1630234.83749542416979.125657335  1630132.843933417137.629933506
1630085.25610167417200.4122882491630007.87600709 417265.38853626
 1629955.3226345417319.2529298371629852.11713226417470.921589762
#Sta/Elev= 30
       0  937.68    20.4  930.27    35.3  920.94    43.6  917.34    58.2  912.54
    72.4  909.89    81.8  906.81   110.3  891.22   133.4   884.6   156.5  873.51
   173.8  868.59   197.2  863.84   237.3  851.32   242.5  848.93   257.4  836.36
   285.2  818.25   298.6  813.96   310.8  811.32   317.2  810.26   326.2  811.33
   336.7   814.1   407.2  818.73   442.4  828.53   469.7   832.5     484  837.12
   496.5  839.02   538.9  854.87   562.6  860.67   595.8  866.56   627.1  875.32
#Mann= 3 ,-1,0
       0      .1       0   310.8    .045       0   326.2      .1       0
Bank Sta=310.8,326.2
XS Rating Curve= 0 ,0
Exp/Cntr(USF)=0,0
Exp/Cntr=0.3,0.1

Type RM Length L Ch R = 1 ,5999    ,497.1,507,515.2
XS GIS Cut Line= 6
1629693.35465451416718.0569537581629644.95186417416892.724255338
1629624.92368901416965.0006855881629578.19051476417133.645361423
1629554.82376359417217.9676993341629529.78772442417308.312663004
#Sta/Elev= 30
       0  891.29    23.3  879.92    60.7  863.04    77.3  859.41   109.5  856.31
   127.1  853.33   156.2  843.74   175.3  835.77   181.1  832.53   204.5   816.8
   210.1  814.39   226.7  812.47   284.8  810.45     289  809.91  299.38805.2324
   309.7  804.27     318  805.23   322.2  806.61   334.6  807.22   350.8  809.24
   389.8  810.98   413.5  815.02   426.7  820.29   442.6   829.6   463.3  843.66
   479.9  856.72   521.4  868.36   546.3   872.5   575.4  880.65   612.5  899.94
#Mann= 3 ,-1,0
       0      .1       0  299.38    .045       0     318      .1       0
Bank Sta=299.38,318
XS Rating Curve= 0 ,0
Exp/Cntr(USF)=0,0
Exp/Cntr=0.3,0.1

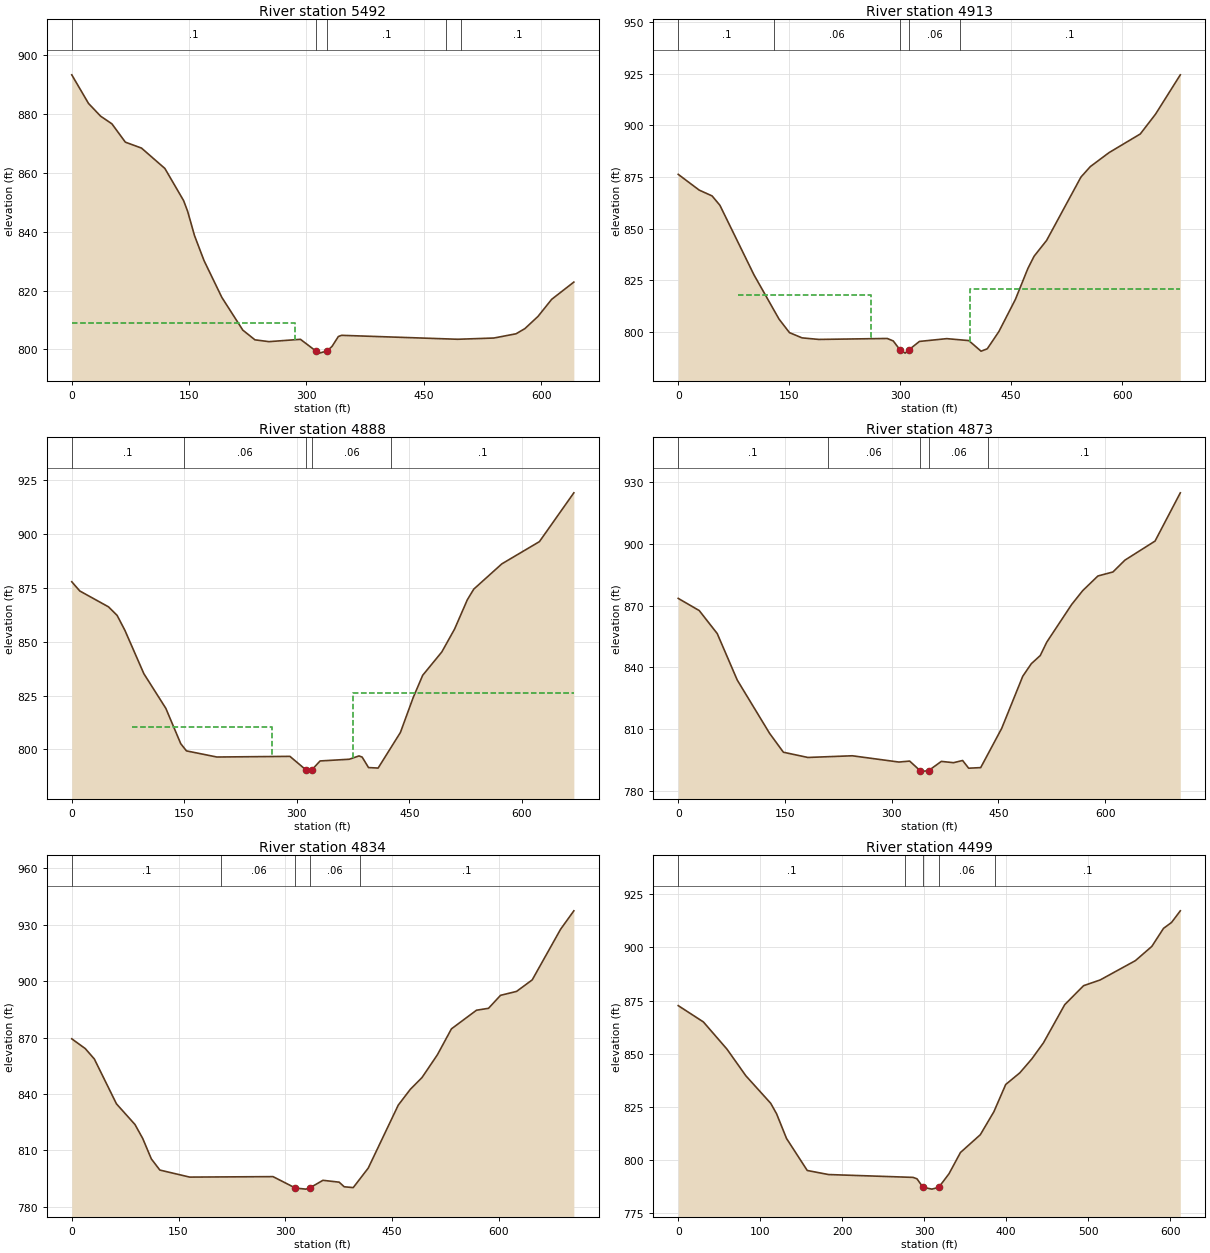
Type RM Length L Ch R = 1 ,5492    ,589.3,579.3,570.2
BEGIN DESCRIPTION:
Structure XS 4
END DESCRIPTION:
XS GIS Cut Line= 6
1629492.37178876416643.7076930111629254.44050609416770.684801251
1629155.01419576416784.524012417 1629083.6944565416815.069226921
1629010.59716175416873.6183224171628940.28496642416945.185764596
#Sta/Elev= 30
       0   893.3    21.4  883.58    36.9  879.25    51.3  876.65    68.5  870.42
    89.1  868.41     119  861.49   142.9  850.58   148.1  846.93   156.9  838.66
   169.1  830.15   191.8  817.68   218.6  806.56   234.1  803.26     252  802.64
   292.3  803.43  311.55799.5513   316.5  798.74   326.6  799.52   326.6  799.53
   332.7  801.05   340.7  804.38   344.8  804.79   493.3  803.45   539.5  803.87
   567.8  805.31   579.1  807.06   595.9  811.22   613.4  817.03   641.7  822.88
#Mann= 5 ,-1,0
       0      .1       0  311.55    .045       0   326.6      .1       0
   477.7     .05       0   497.7      .1       0
#XS Ineff= 2 , 0
          285.84  808.93
Permanent Ineff=
       F       F
Bank Sta=311.55,326.6
XS Rating Curve= 0 ,0
Exp/Cntr(USF)=0,0
Exp/Cntr=0.3,0.1

Type RM Length L Ch R = 1 ,4913    ,20.2,24.3,22.7
BEGIN DESCRIPTION:
Structure XS 3
END DESCRIPTION:
XS GIS Cut Line= 6
1628945.28384442416265.1417645571628755.01579051 416442.52708565
1628750.06089327416468.2925512841628747.08795493416512.886626419
1628746.09697548416542.6160098421628444.83922346416643.695913482
#Sta/Elev= 30
       0  876.27    28.4  868.65    45.7  865.87    56.3  861.35   102.3  827.77
   136.2  806.36   150.4  799.79   167.4  797.27     190  796.52   282.5  796.98
   290.6  795.79   299.7  791.51   306.7   789.9  311.85791.5248     326  795.55
   362.9   796.9   392.7  795.96   409.3  790.84   417.7  791.99   433.4  800.33
   455.7  815.85   472.6  830.81     481  836.73   497.9  844.36   544.3  874.96
     557  880.03   582.3  886.78   624.5  895.79   645.1  905.35   678.6  924.36
#Mann= 5 ,-1,0
       0      .1       0     130     .06       0   299.7    .045       0
  311.85     .06       0  380.81      .1       0
#XS Ineff= 2 ,-1
   81.02  260.68  818.11  394.54678.5696  820.83
Permanent Ineff=
       F       F
Bank Sta=299.7,311.85
XS Rating Curve= 0 ,0
Exp/Cntr(USF)=0,0
Exp/Cntr=0.3,0.1

Type RM Length L Ch R = 1 ,4888    ,19.4,15.9,14
BEGIN DESCRIPTION:
Structure XS 2
END DESCRIPTION:
XS GIS Cut Line= 6
1628939.92725228416251.0002556921628734.79450666416442.259289049
1628732.81254777416458.1149602091628727.85765053416492.799240869
1628727.85765053 416527.483521531628442.45556966416629.554404617
#Sta/Elev= 30
       0  877.82    10.7  873.54      49  866.17    60.4  862.24    70.8  855.31
    96.1  835.16   125.4  819.07   145.3  802.66   152.9  799.33   193.4  796.49
   290.8  796.79   312.6   790.4   315.1  789.94  319.69  790.39     331  794.66
   369.9  795.45   382.9     797   387.1  796.45   395.6  791.59   408.4  791.36
   438.1  807.88   455.1  824.06   467.8  834.41   493.3  845.25   510.3  855.86
   527.3  869.45   535.9   874.4   573.3  886.12   623.4  896.44   669.3  919.09
#Mann= 5 ,-1,0
       0      .1       0     150     .06       0   312.6    .045       0
  319.69     .06       0  426.16      .1       0
#XS Ineff= 2 ,-1
   80.01  266.71  810.24  375.41 669.268  826.07
Permanent Ineff=
       F       F
Bank Sta=312.6,319.69
XS Rating Curve= 0 ,0
Exp/Cntr(USF)=0,0
Exp/Cntr=0.3,0.1

Type RM Length L Ch R = 1 ,4873    ,44.5,38.1,36.5
XS GIS Cut Line= 5
1628894.08422425416217.150365505 1628690.6196879416399.795274878
1628717.11739496416444.2735688711628722.79547504416494.429942947
1628410.50107041416600.420771185
#Sta/Elev= 30
       0  873.46    29.5  867.55    54.8  856.37    82.9  833.79   128.4  807.86
   147.8  798.69   182.2  796.15   244.6  796.97   310.1  793.92   325.2  794.39
  339.82  789.76   345.6  789.51   351.8  789.76   369.7  794.24   386.9  793.61
   399.6  794.68   408.1  790.93     425  791.22   454.5  810.28   484.1  835.61
   496.1  841.71   508.7  845.69   517.9  852.23   552.9  870.53   568.4  877.25
   589.7  884.35   610.8   886.3   627.7  892.06     670  901.32   705.5  924.77
#Mann= 5 ,-1,0
       0      .1       0     210     .06       0  339.82    .045       0
   351.8     .06       0  435.67      .1       0
Bank Sta=339.82,351.8
XS Rating Curve= 0 ,0
Exp/Cntr(USF)=0,0
Exp/Cntr=0.3,0.1

Type RM Length L Ch R = 1 ,4834    ,324.3,335.5,346.3
XS GIS Cut Line= 5
1628866.16699717416213.8381521231628662.70246082416396.483061496
1628689.20016788416440.9613554881628694.87824796416491.117729565
1628382.58384333416597.108557802
#Sta/Elev= 30
       0  869.36    18.9  864.18    31.7  858.63    62.8  834.75    88.8  823.77
    99.7  816.33   111.8  805.46   123.8  799.51   165.7  795.77   282.8  796.02
  314.28  789.95   328.8  789.37  334.19  789.95   352.9  794.06   375.7  793.08
   382.8  790.63   395.5  790.18   416.6  800.57   458.8  834.09   475.7  842.47
   492.1  848.73   513.8  860.89   533.5  874.66   568.7  884.58   585.6   885.6
   602.5   892.5     625  894.59     647  900.72   686.9  927.68   705.5  937.47
#Mann= 5 ,-1,0
       0      .1       0     210     .06       0  314.28    .045       0
  334.19     .06       0  405.67      .1       0
Bank Sta=314.28,334.19
XS Rating Curve= 0 ,0
Exp/Cntr(USF)=0,0
Exp/Cntr=0.3,0.1

Type RM Length L Ch R = 1 ,4499    ,497.8,500,502.1
BEGIN DESCRIPTION:
Structure XS 1
END DESCRIPTION:
XS GIS Cut Line= 6
1628701.15125833 416038.824388341628623.91650468416091.972247928
1628489.16152485416182.7870269271628344.03943975416280.585715845
1628271.71445318416329.835617334 1628195.4048945416384.355849504
#Sta/Elev= 30
       0   872.6    30.7  864.93    59.5  852.12    82.5   839.6   112.8  826.68
     120  821.72   132.1  810.13   157.4  795.07   183.3  793.16   286.5  791.82
   291.3  791.14   298.6  787.16   309.5   786.3   317.8787.1436   330.3  793.52
   344.3  803.53   368.5  811.88   385.1  822.73   399.5  835.51   416.8  841.03
   431.3  847.52   445.6  855.14   471.5  873.07   494.5  881.99   514.7  884.67
   557.8  893.78   577.8  900.48     592  908.94   601.8  911.72   612.5  917.19
#Mann= 5 ,-1,0
       0      .1       0  276.25     .06       0   298.6    .045       0
   317.8     .06       0  386.25      .1       0
Bank Sta=298.6,317.8
XS Rating Curve= 0 ,0
Exp/Cntr(USF)=0,0
Exp/Cntr=0.3,0.1

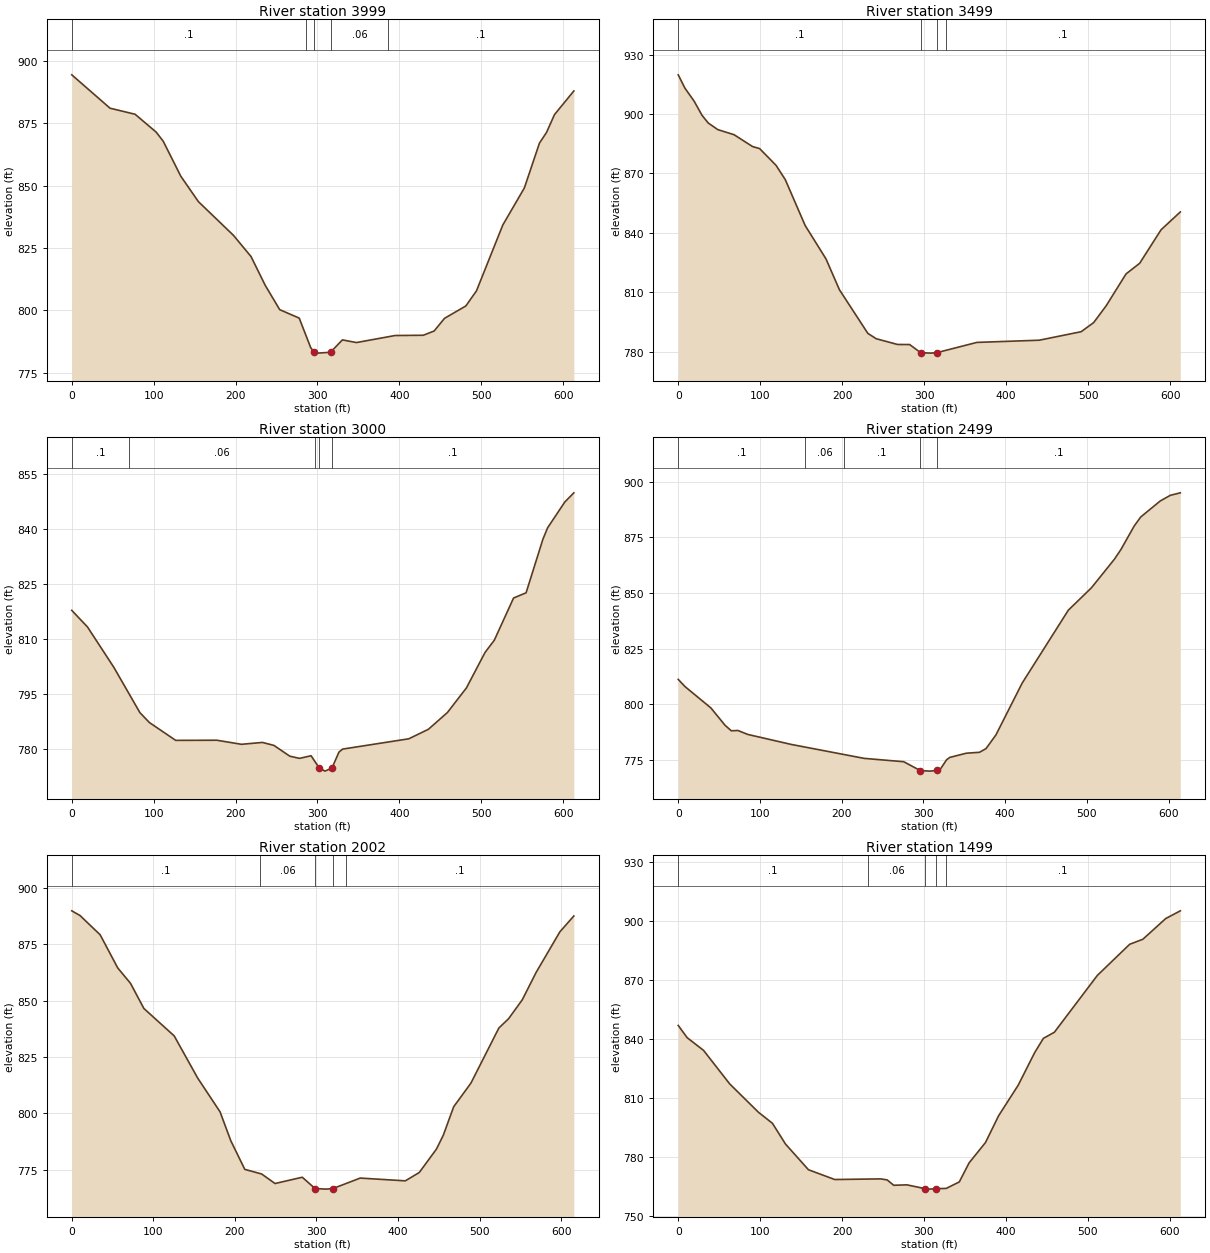
Type RM Length L Ch R = 1 ,3999    ,505.3,500,494.7
XS GIS Cut Line= 6
1628540.24770875415652.2949776651628371.21950351415717.724964917
1628208.02002676415780.8990511751628138.07758135 415807.97314401
1628057.25458026415841.7604780051627969.96374434415877.062900841
#Sta/Elev= 30
       0  894.32    46.7  880.96    77.3  878.54   103.1  871.37   111.7  867.72
   133.1  853.75   154.6  843.56   197.4  830.07   218.9  821.56   236.1   810.1
   253.9  800.31   277.7  796.93   291.8  785.05   296.1  783.26   300.4  782.91
  315.92  783.26   330.4  788.21   347.6  787.14   394.8  789.96   429.1  790.06
   442.4  791.76   455.1  796.84   481.1  801.78   494.1  807.82   526.3  834.22
   552.6  849.04     571  866.97   579.6  871.24   589.4  878.41     613  887.86
#Mann= 5 ,-1,0
       0      .1       0  286.25     .06       0   296.1    .045       0
  315.92     .06       0  386.25      .1       0
Bank Sta=296.1,315.92
XS Rating Curve= 0 ,0
Exp/Cntr(USF)=0,0
Exp/Cntr=0.3,0.1

Type RM Length L Ch R = 1 ,3499    ,498.1,499.4,500.4
XS GIS Cut Line= 6
1628170.09982701415111.0992096661628057.65287343415253.251484424
1628011.12245467415312.0725610111627949.08288059415390.501538008
1627902.55278993415449.3226145951627790.10583635415591.474889338
#Sta/Elev= 30
       0  919.79     8.1  913.11    19.5  906.43      29  899.37    36.6  895.47
    48.3  892.13    68.1  889.57    90.7  883.58    99.3  882.56   119.3  874.12
   130.6   866.9   154.8  843.77   180.3  826.85   196.6  811.35   231.3   789.3
   241.5  786.59   267.5  783.69   282.3  783.65   295.7  779.58   307.8  779.32
   315.7  779.58   364.3  784.73   440.4  785.84   491.5  790.13   506.8  794.73
   522.1  803.24   546.3  819.31   562.9  824.66     589  841.57   612.5  850.58
#Mann= 4 ,-1,0
       0      .1       0   295.7    .045       0   315.7     .06       0
  326.25      .1       0
Bank Sta=295.7,315.7
XS Rating Curve= 0 ,0
Exp/Cntr(USF)=0,0
Exp/Cntr=0.3,0.1

Type RM Length L Ch R = 1 ,3000    ,493.1,500.3,505.3
XS GIS Cut Line= 6
1627891.73719476414731.365717173 1627823.3980926414795.999774262
1627765.15575501 414861.299840511627598.75221643 415047.87394242
1627538.34879392 415111.246191011627472.38895209415178.038052171
#Sta/Elev= 30
       0  817.84    19.2  813.32    51.5  802.27    83.2  789.97    94.8  787.27
   126.9  782.41   177.1  782.45   207.2  781.34   232.8  781.85   246.9  781.03
   266.3  778.09   278.1  777.51   292.2  778.22  302.11774.9019   309.2  774.03
   317.7  774.88   326.2   779.2   330.6  780.03   411.5  782.84   435.4  785.43
   458.6  789.99   481.8  796.69   504.6  806.38   515.9  809.71   539.4   821.2
   554.7  822.63   575.3  837.28     581  840.35     602  847.38     613  849.87
#Mann= 5 ,-1,0
       0      .1       0      70     .06       0  296.56      .1       0
  302.11    .045       0   317.7      .1       0
Bank Sta=302.11,317.7
XS Rating Curve= 0 ,0
Exp/Cntr(USF)=0,0
Exp/Cntr=0.3,0.1

Type RM Length L Ch R = 1 ,2499    ,498.5,497.6,494.5
XS GIS Cut Line= 6
1627836.17037676414446.7649084181627742.47207335 414462.20385392
1627656.15269217414479.1316415821627581.87167276414489.869809091
1627482.54050659414501.4160458451627228.03379776414531.144004762
#Sta/Elev= 30
       0   811.2     8.2     808    39.9   798.4    57.3  790.59    64.9  788.12
      73  788.26    85.1  786.48   138.1  782.01   227.4  775.74   275.9  774.23
     296  770.28   308.1  770.01  317.08770.3384   320.2  770.62   328.2  775.07
   332.2  776.17   352.4  778.06   368.5  778.46   376.5  780.11   388.6  786.24
   420.8  809.57   477.2  842.27   505.4   852.3   533.6  865.17   541.6  869.55
   557.8  880.08   565.8  884.13   589.7  891.33   602.1  893.86   614.2  894.97
#Mann= 5 ,-1,0
       0      .1       0  154.96     .06       0  202.93      .1       0
     296    .045       0  317.08      .1       0
Bank Sta=296,317.08
XS Rating Curve= 0 ,0
Exp/Cntr(USF)=0,0
Exp/Cntr=0.3,0.1

Type RM Length L Ch R = 1 ,2002    ,501.3,502.8,503.1
XS GIS Cut Line= 6
1627809.92075734413925.9336010071627561.32151701413988.082098752
1627465.45294234414017.1315813361627394.10400367414043.111844346
1627310.14616634414071.0852135871627219.76248884 414099.26232259
#Sta/Elev= 30
       0  889.91    10.1  887.83    34.8  879.27    56.4  864.52      72  857.72
    88.4  846.55   125.6  834.35   154.4  815.62   181.8  800.63   194.9  787.85
   212.1  775.09   232.8  773.03   249.2   768.8   282.6  771.59  298.21766.5831
   311.8  766.31   320.2  766.57   353.6  771.22   408.9  769.99     426  773.69
   447.1  784.11   455.5  790.28   468.2   802.9   489.3  813.37   523.6  837.87
   535.5  841.99   552.3  850.41   569.1  862.45   598.4   880.6   615.5  887.62
#Mann= 5 ,-1,0
       0      .1       0  231.25     .06       0  298.21    .045       0
   320.2     .06       0  336.25      .1       0
Bank Sta=298.21,320.2
XS Rating Curve= 0 ,0
Exp/Cntr(USF)=0,0
Exp/Cntr=0.3,0.1

Type RM Length L Ch R = 1 ,1499    ,499.9,499.6,494.1
XS GIS Cut Line= 6
1627619.00184783413543.7207827571627525.08536901413547.521628171
1627437.47694843413551.4871714261627362.38851592413554.923516259
1627262.38248233413558.938928172   1627006.39743413567.318176508
#Sta/Elev= 30
       0  846.93    10.9   840.7    30.9  834.24    62.9  817.15    98.1  802.68
     115  797.14     131  786.55     159  773.48   191.1  768.49   247.1  768.81
   255.1   768.3   263.1  765.56   279.2  765.78  301.27763.8589   307.2   763.6
   315.2  763.84   327.2  763.96   343.2  767.26   355.2  776.97   375.2  787.32
   391.2  800.94   415.2  816.55   435.3  833.13   445.9  840.36   459.3  843.46
   511.8   872.4   551.3  888.26   567.3  890.79   595.3  901.35   613.1  905.28
#Mann= 5 ,-1,0
       0      .1       0  231.69     .06       0  301.27    .045       0
   315.2     .06       0  326.86      .1       0
Bank Sta=301.27,315.2
XS Rating Curve= 0 ,0
Exp/Cntr(USF)=0,0
Exp/Cntr=0.3,0.1