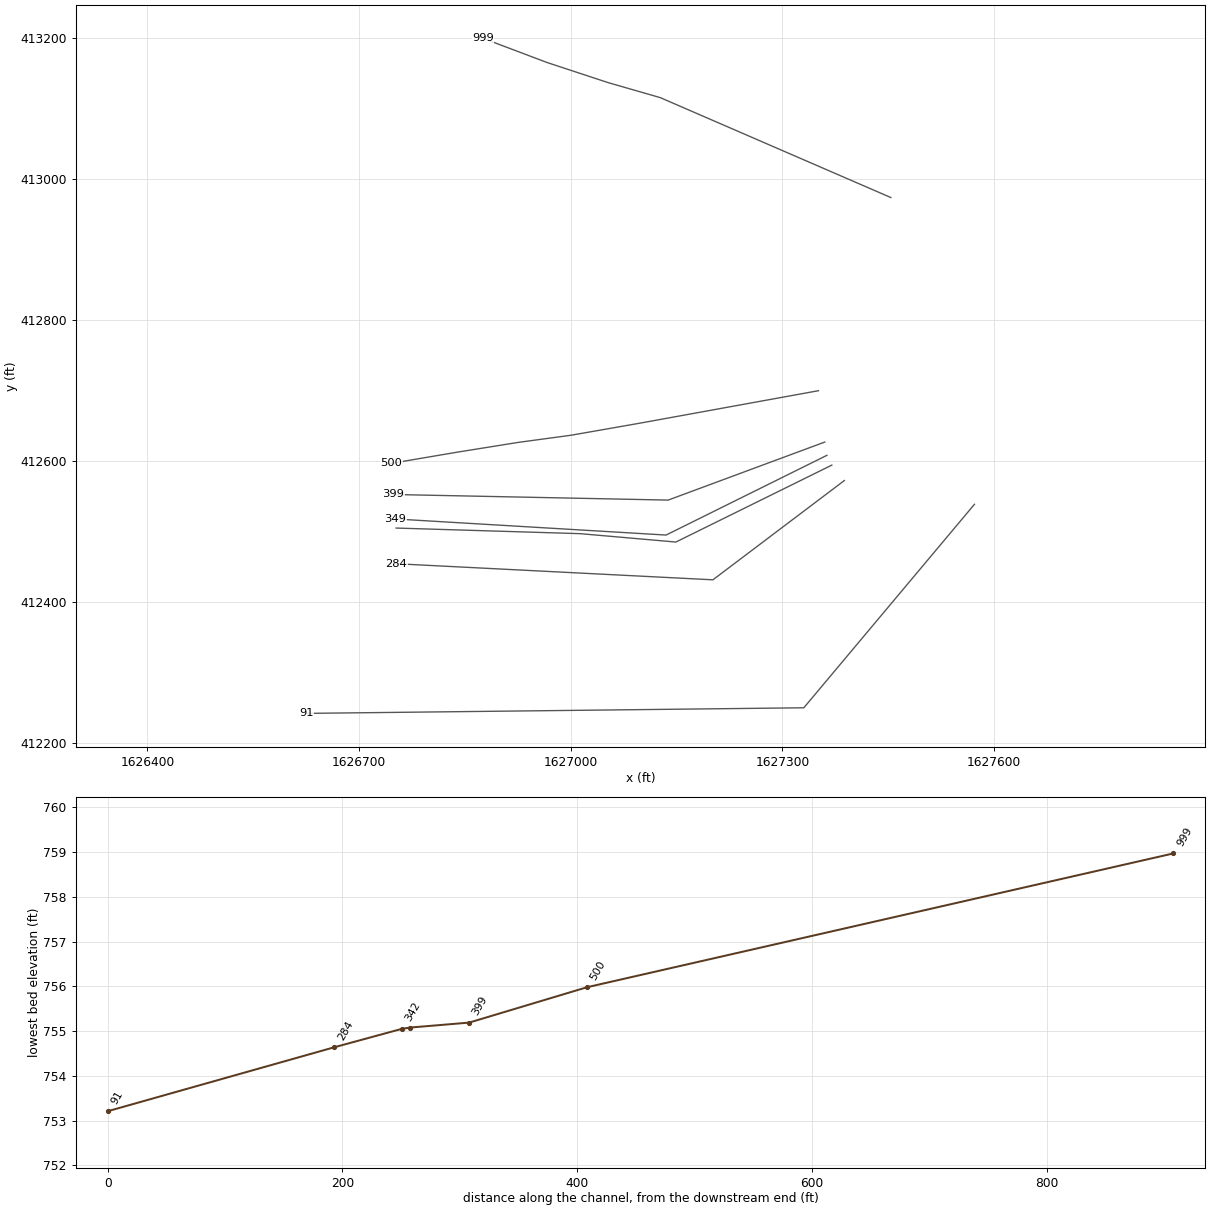
HEC-RAS study SCHDLRRN.prj: SCHDLRRN

--- SCHDLRRN.g01 (geometry) --- (continued)

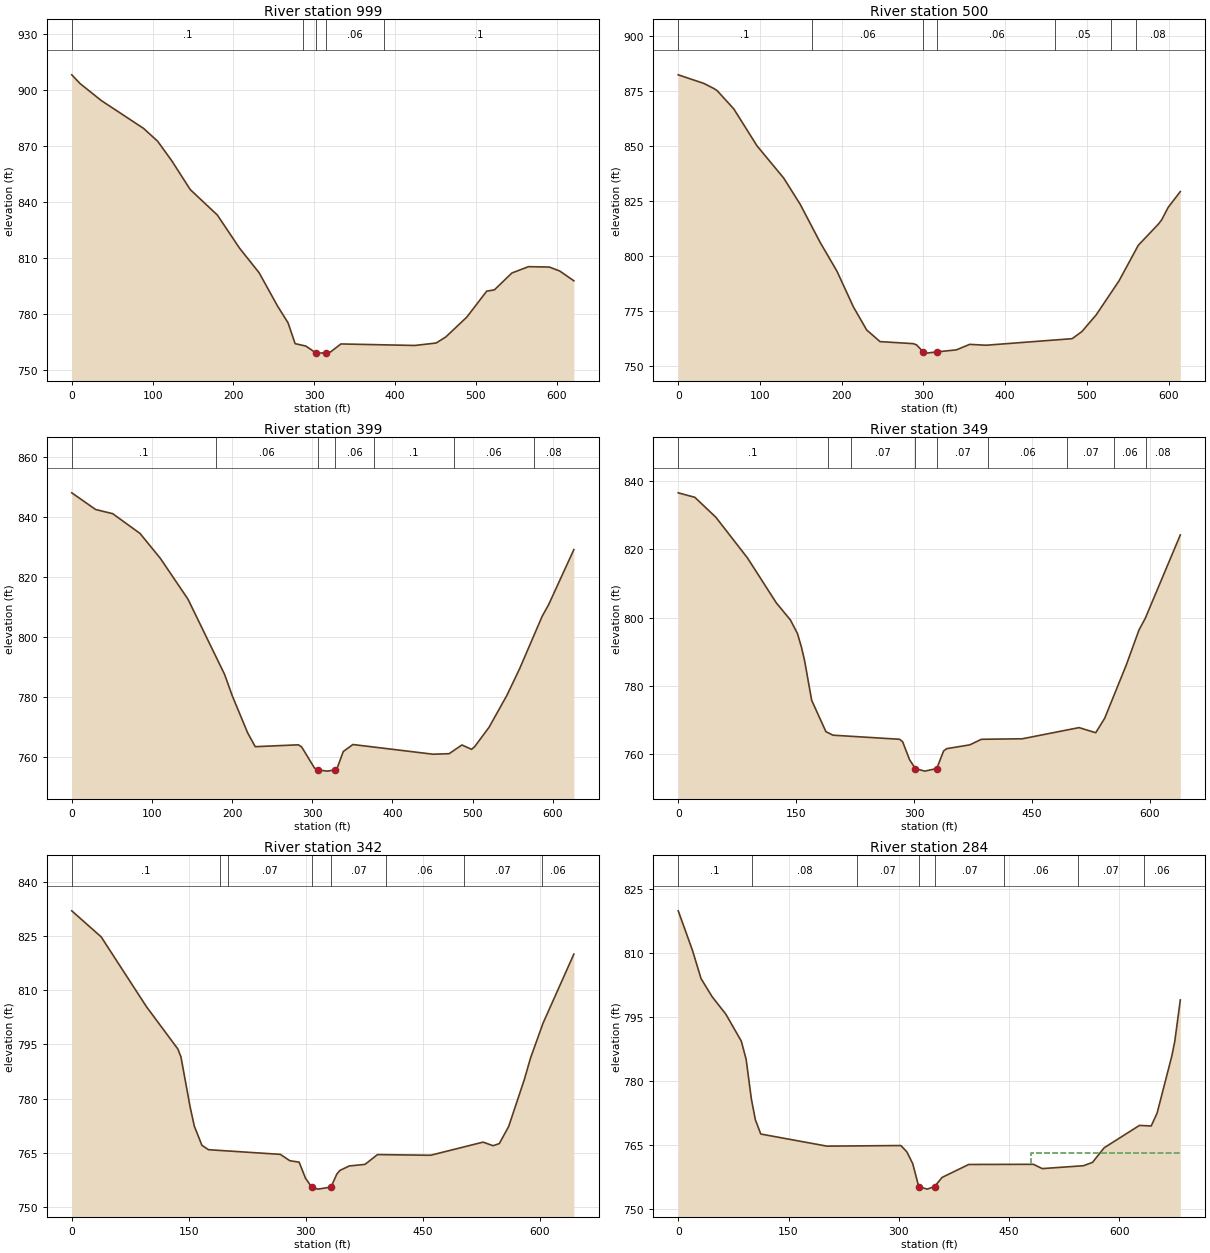
Type RM Length L Ch R = 1 ,999     ,495.9,499.7,505.3
XS GIS Cut Line= 6
1627453.64719167412973.2261888381627367.62636635413010.502032921
1627126.76825225413114.874855667 1627052.9150535413136.126453593
1626966.64061975413164.5312524291626875.74644458413198.849097177
#Sta/Elev= 30
       0  908.26    10.4  903.53    36.5  894.47    88.9   879.5   106.3  872.61
   123.7  862.16   146.6  846.69   180.1  833.05   207.5  815.31   231.8  802.07
   254.5  784.27   267.6  775.19   276.3  764.05   289.6  762.76   301.7  759.16
   306.8  758.97   313.9   759.2     320  759.57     333  763.89   424.4  763.08
   450.8   764.4   462.6  767.61   488.7  778.29   513.3  792.21   522.8   792.9
   544.5  801.97   565.1  805.36   590.8  805.14   603.6  803.03   621.1  797.78
#Mann= 5 ,-1,0
       0      .1       0  286.25     .06       0   301.7    .045       0
   313.9     .06       0  386.25      .1       0
Bank Sta=301.7,313.9
XS Rating Curve= 0 ,0
Exp/Cntr(USF)=0,0
Exp/Cntr=0.3,0.1

Type RM Length L Ch R = 1 ,500     ,101.7,100.4,97.5
BEGIN DESCRIPTION:
Structure 2 XS 4
END DESCRIPTION:
XS GIS Cut Line= 6
1627351.02830243412699.4954370861627098.91168067412653.655961841
1627000.41154958 412636.389920251626925.89529443412626.300045416
1626838.77801459412612.3381310851626745.52032709412596.516312346
#Sta/Elev= 30
       0  882.49    31.4  878.58    43.6  876.27    47.7  875.26      68  866.99
    96.5  850.15     129  835.58   149.3  823.58   173.7  806.28   194.3  793.16
   214.4  776.94   230.6  766.48   246.9  761.22   287.5  760.29   291.6  759.74
   299.7  756.56   303.8  755.98   317.1  756.57   340.3  757.46   356.6  759.96
   376.7  759.57   481.9  762.55   493.9  765.78   511.4  773.39   539.2  788.76
     563  805.06   587.3  814.55   591.4  816.51   599.5  822.26   614.3  829.41
#Mann= 7 ,-1,0
       0      .1       0  163.75     .06       0   299.7    .045       0
   317.1     .06       0  461.45     .05       0  529.68     .06       0
  559.68     .08       0
Bank Sta=299.7,317.1
XS Rating Curve= 0 ,0
Exp/Cntr(USF)=0,0
Exp/Cntr=0.3,0.1

Type RM Length L Ch R = 1 ,399     ,52.2,50,49.4
BEGIN DESCRIPTION:
Structure 2 XS 3
END DESCRIPTION:
XS GIS Cut Line= 3
1627360.05026642 412626.746797021627138.07087019412544.495502882
1626748.61594734412552.423338462
#Sta/Elev= 30
       0  848.06    29.8  842.49    51.1   841.1    85.2  834.49   110.6  826.16
     145  812.55   190.6  787.49   200.4  780.21   219.5  767.91   228.9  763.35
   282.7  763.97   286.7  763.29   302.7  756.26   306.7  755.61   318.7  755.19
   328.9  755.62   330.7  755.92   338.7  761.74   350.7  764.07   450.7  760.83
   470.7  761.01   486.7  763.92   498.7  762.46   502.7   763.4   520.5  769.81
   542.7  780.43   558.8  789.45   586.8  806.88   594.8  810.71   626.3  829.11
#Mann= 7 ,-1,0
       0      .1       0     180     .06       0   306.7    .045       0
   328.9     .06       0  376.73      .1       0  476.73     .06       0
  576.73     .08       0
Bank Sta=306.7,328.9
XS Rating Curve= 0 ,0
Exp/Cntr(USF)=0,0
Exp/Cntr=0.3,0.1

Type RM Length L Ch R = 1 ,349     ,7.4,7.4,7.3
BEGIN DESCRIPTION:
Structure 2 XS 2
END DESCRIPTION:
XS GIS Cut Line= 3
1627363.02320476412607.9181875191627135.09793185 412494.94653051
1626751.58888568412517.739057801
#Sta/Elev= 30
       0  836.55    21.1  835.24    47.9  829.39    88.1  817.48   124.7  804.35
   142.7  799.33   151.7  795.33   156.9   791.2   160.7  787.46   169.7  775.83
   187.8  766.65   196.8   765.6   281.4  764.41   285.4   763.7   294.2  758.45
   301.5  755.84   313.5  755.08  328.81 755.832   337.5  760.97   341.5  761.66
   370.9  762.77   385.6   764.4   437.7  764.55   509.8  767.82     531  766.32
   542.4  770.55   569.9  786.17     586  796.38     594   799.8   638.6  824.22
#Mann= 9 ,-1,0
       0      .1       0     190     .06       0     220     .07       0
   301.5    .045       0  328.81     .07       0  394.39     .06       0
  494.39     .07       0  554.39     .06       0  594.39     .08       0
Bank Sta=301.5,328.81
XS Rating Curve= 0 ,0
Exp/Cntr(USF)=0,0
Exp/Cntr=0.3,0.1

Type RM Length L Ch R = 1 ,342     ,57.6,57.4,59.8
BEGIN DESCRIPTION:
Structure 1 XS 3
END DESCRIPTION:
XS GIS Cut Line= 4
1627369.96006089412594.0444752541627148.97164411412485.036736035
1627013.20745981412496.9284894051626752.57986513412504.856324984
#Sta/Elev= 30
       0  831.91    37.7  824.71    95.7  805.44   135.9  793.77   139.9  791.58
   151.8   777.6   157.1   772.4   166.8  767.15   175.2  765.94   267.3  764.65
   279.4   762.9   291.4  762.49   299.5  758.08   307.5  755.59   315.5  755.05
  332.19755.6112   339.6  759.18   343.6  760.21   355.7  761.45   375.8  761.89
   391.8  764.59   459.8   764.4   527.1  768.03   539.9  767.04   547.9  767.63
   559.9  772.36   579.9  785.29   587.9  791.26   603.9  800.87   643.4  819.95
#Mann= 8 ,-1,0
       0      .1       0     190     .08       0     200     .07       0
   307.5    .045       0  332.19     .07       0   402.7     .06       0
   502.7     .07       0   602.7     .06       0
Bank Sta=307.5,332.19
XS Rating Curve= 0 ,0
Exp/Cntr(USF)=0,0
Exp/Cntr=0.3,0.1

Type RM Length L Ch R = 1 ,284     ,192.6,193.2,193.8
BEGIN DESCRIPTION:
Structure 1 XS 2
END DESCRIPTION:
XS GIS Cut Line= 3
1627387.79769095412572.2429274111627201.49355483412431.523845873
1626752.57986513412454.316373164
#Sta/Elev= 30
       0   819.9    19.4  810.62      31  804.02      46  799.79    64.8  795.66
    85.8  789.34    92.4  785.05    99.5  775.77   104.9  770.92   112.3  767.56
   202.3  764.72   302.9  764.86     311  763.38     319  760.61   327.2  755.23
   338.7  754.64  348.62755.2353     359  757.39   395.1  760.42   483.2  760.46
   495.2  759.45   551.3  760.13   563.6  760.92   579.3  764.32   627.4  769.58
   643.4  769.45   651.4  772.45   671.4  785.82   675.4  789.21     683     799
#Mann= 8 ,-1,0
       0      .1       0     100     .08       0  243.48     .07       0
   327.2    .045       0  348.62     .07       0  443.48     .06       0
  543.48     .07       0  633.48     .06       0
#XS Ineff= 2 , 0
                          479.58          763.05
Permanent Ineff=
       F       F
Bank Sta=327.2,348.62
XS Rating Curve= 0 ,0
Exp/Cntr(USF)=0,0
Exp/Cntr=0.3,0.1

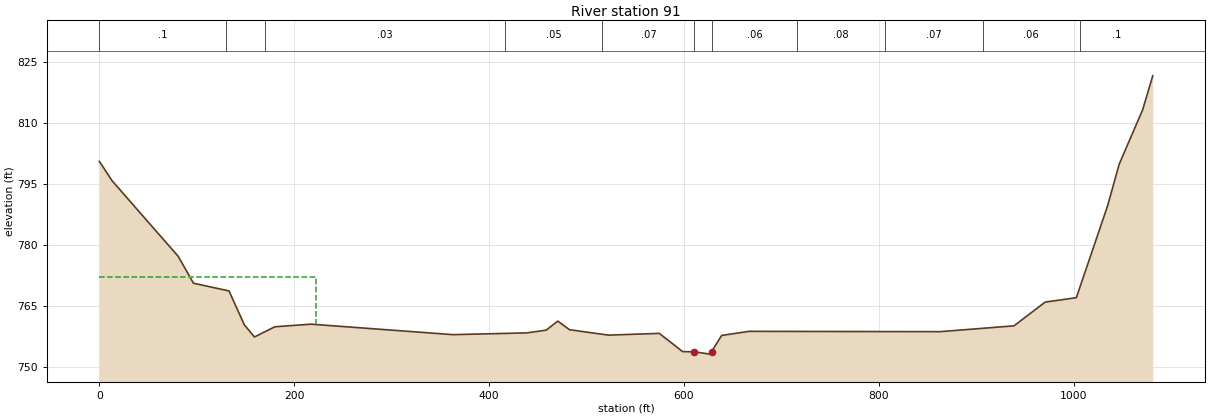
Type RM Length L Ch R = 1 ,91      ,,,
BEGIN DESCRIPTION:
Structure 1 XS 1
END DESCRIPTION:
XS GIS Cut Line= 3
1627572.11986817412538.5496261971627330.32088299 412250.17460699
1626625.73449586412242.246771411
#Sta/Elev= 30
       0  800.52    13.1  795.74    80.9  777.22    96.6  770.61   133.1  768.71
   148.8  760.39   159.2  757.42   180.1  759.92   217.2  760.56   362.8  757.99
   438.5  758.42   458.5  759.09   470.5  761.31   482.5   759.2   522.5  757.87
   574.6   758.3   598.6  753.83   610.6  753.78   626.6  753.21  628.21753.8094
   638.6  757.79   666.6   758.8   862.7  758.72   938.6  760.15   970.6  765.97
  1002.6  767.06  1034.6  789.54  1046.6  799.83  1070.6  813.12    1081  821.49
#Mann= 11 ,-1,0
       0      .1       0     130     .06       0     170     .03       0
  416.33     .05       0  516.33     .07       0   610.6    .045       0
  628.21     .06       0  716.33     .08       0  806.33     .07       0
  906.33     .06       0 1006.33      .1       0
#XS Ineff= 2 , 0
          222.57  772.21
Permanent Ineff=
       F       F
Bank Sta=610.6,628.21
XS Rating Curve= 0 ,0
Exp/Cntr(USF)=0,0
Exp/Cntr=0.3,0.1
LCMann Table=0

Chan Stop Cuts=-1
Use User Specified Reach Order=0
Composite Channel Slope=5